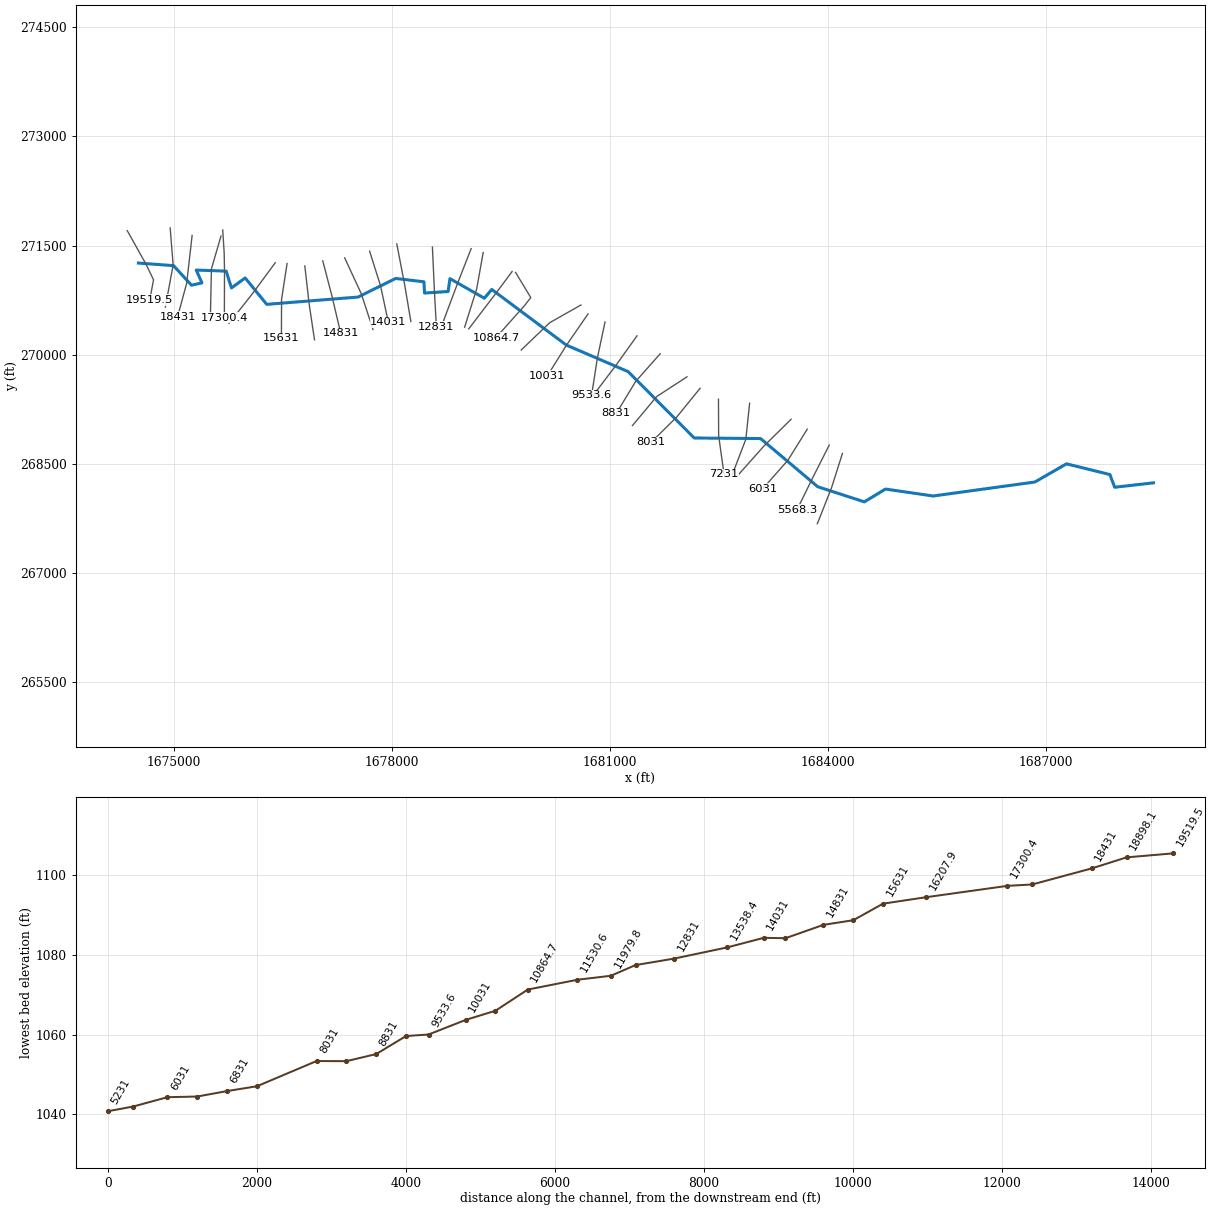
--- CoburnFk.prj (project) ---

Proj Title=CoburnFk
Current Plan=p01
Default Exp/Contr=0,0
English Units
Geom File=g01
Flow File=f01
Plan File=p01
BEGIN DESCRIPTION:
END DESCRIPTION:
DSS Export Rating Curves= 0
DSS Export Rating Curve Sorted= 0
DSS Export Volume Flow Curves= 0
DXF OffsetX= 0
DXF OffsetY= 0
DXF ScaleX= 0
DXF ScaleY= 0

--- CoburnFk.p01 (plan) ---

Plan Title=Floodplain
Program Version=4.00
Geom File=g01
Flow File=f01
K Sum by GR=0
Std Step Tol=0.01
Critical Tol=0.01
Num of Std Step Trials=20
Max Error Tol=0.3
Flow Tol Ratio=0.001
Split Flow NTrial=30
Split Flow Tol=0.02
Split Flow Ratio=0.02
Log Output Level=0
Friction Slope Method=1
Unsteady Friction Slope Method=2
Unsteady Bridges Friction Slope Method=1
Global Log Level=0
CheckData=False
Run HTab=0
Run UNet=0
Run PostProcess=0
UNET Theta=0
UNET Theta Warmup=0
UNET ZTol=0
UNET ZSATol=0
UNET MxIter=0
UNET MaxInSteps=0
UNET DtIC=0
UNET DtMin=0
UNET MaxCRTS=0
UNET WFStab=0
UNET SFStab=0
UNET WFX=0
UNET SFX=0
UNET DSS MLevel=0
UNET DZMax Abort=0
UNET Convert EG Bridges=0
UNET Use Existing IB Tables=0
UNET Froude Limit=0
UNET Froude Power=0
Write IC File=0
Echo Input=False
Echo Output=False
Write Detailed=0

--- CoburnFk.f01 (steady flow) ---

Flow Title=NFF Regression Equation
Program Version=4.00
Number of Profiles=1
Profile Names=P100yr
River Rch & RM=CoburnFk,Main      ,19519.5
709.0545
River Rch & RM=CoburnFk,Main      ,18898.1
780.4385
River Rch & RM=CoburnFk,Main      ,17300.4
792.5736
River Rch & RM=CoburnFk,Main      ,16207.9
881.7333
River Rch & RM=CoburnFk,Main      ,15631
950.9706
River Rch & RM=CoburnFk,Main      ,14031
986.0567
River Rch & RM=CoburnFk,Main      ,10864.7
1080.066
River Rch & RM=CoburnFk,Main      ,10431
1217.462
River Rch & RM=CoburnFk,Main      ,9533.6
1226.441
River Rch & RM=CoburnFk,Main      ,9231
1480.518
River Rch & RM=CoburnFk,Main      ,6031
1583.112
River Rch & RM=CoburnFk,Main      ,195.1
1747.837
Boundary for River Rch & Prof#=CoburnFk,Main      ,1
Up Type=0
Dn Type=3
Dn Slope=0.003284

--- CoburnFk.g01 (geometry) ---

Geom Title=USGS 3m DEM
Program Version=4.00

River Reach=CoburnFk        ,Main
Reach XY= 30
     1674516.273      271259.624     1674999.306      271224.064
     1675246.078      270955.656     1675389.727         270987.
     1675311.368       271163.47     1675723.258      271148.684
     1675795.971      270917.594     1675984.868       271054.72
     1676280.999      270692.063     1677537.571      270792.376
     1678054.998      271048.172     1678444.226      271002.082
     1678452.083      270847.837     1678776.809      270868.468
     1678801.533      271045.594     1679274.961      270776.276
     1679376.907      270896.794     1680402.621      270132.327
     1681253.449       269767.02     1682162.051       268854.67
     1683074.915      268847.145     1683861.833      268184.262
     1684502.308      267977.021     1684793.535      268152.694
     1685449.098      268057.415     1686848.394      268249.647
     1687283.676      268499.479     1687880.367      268352.501
     1687946.091       268177.66     1688480.774      268238.216

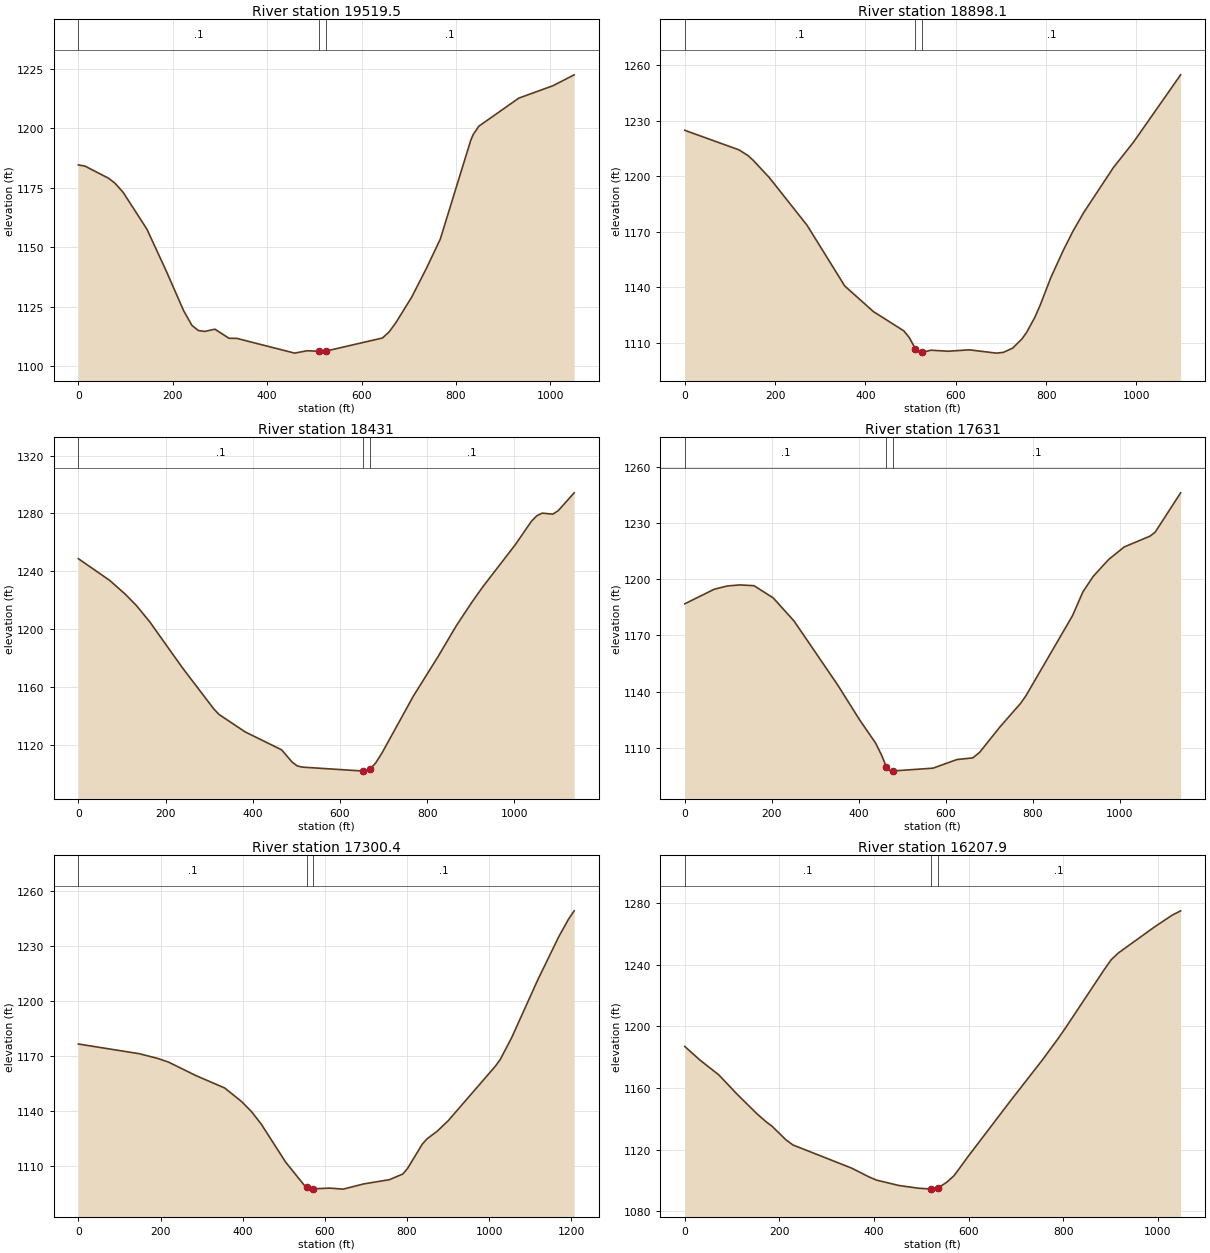
Type RM Length L Ch R = 1 ,19519.5 ,544.963,621.342,532.262
XS GIS Cut Line= 4
     1674362.116      271705.656     1674617.198       271249.96
     1674723.922      271029.899     1674671.918      270751.116
#Sta/Elev= 30
       0 1184.51    13.9 1184.02    63.7 1178.95    77.3 1176.89    94.9 1172.99
   145.3 1157.51   186.2 1139.96   223.2 1123.22   240.6 1117.11   254.2 1114.93
   267.8 1114.56   289.4 1115.49   319.2 1111.68   335.8 1111.63   458.3 1105.44
   484.9 1106.45   510.2 1106.21   525.2 1106.33   644.2 1111.79   658.1 1114.28
   672.9 1118.28   706.4 1129.03   737.3 1141.01   766.8 1153.34   831.3 1194.83
   836.4 1197.22   848.5 1200.77   933.1 1212.56  1005.5 1217.77  1050.4 1222.35
#Mann= 3 , 0 , 0
       0      .1       0   510.2    .045       0   525.2      .1       0
Bank Sta=510.2,525.2
XS Rating Curve= 0 ,0
Exp/Cntr=0.3,0.1

Type RM Length L Ch R = 1 ,18898.1 ,422.558,467.161,463.627
XS GIS Cut Line= 3
     1674952.839      271741.803     1674993.621      271233.114
     1674886.891      270655.539
#Sta/Elev= 30
       0 1224.94   119.9 1214.37   139.7 1211.32   151.6 1208.69   187.3 1199.32
   270.7 1173.59   354.1 1140.77   417.7 1126.89   485.1 1116.46     497 1112.86
   510.3 1106.91     521 1104.48   525.3 1104.84   545.1 1106.03   583.3 1105.47
   629.6 1106.23     690 1104.45   705.6 1104.88     726 1107.18   746.4 1112.12
   756.6 1115.61   774.5  1123.6   786.6 1130.29   810.7 1145.49   838.1 1160.11
     859 1170.21   883.2 1180.49   948.7 1204.74   993.1 1218.45  1097.7 1254.94
#Mann= 3 , 0 , 0
       0      .1       0   510.3    .045       0   525.3      .1       0
Bank Sta=510.3,525.3
XS Rating Curve= 0 ,0
Exp/Cntr=0.3,0.1

Type RM Length L Ch R = 1 ,18431   ,762.716,800,775.457
XS GIS Cut Line= 3
     1675254.694      271638.348     1675179.819      270982.067
     1675055.099      270522.388
#Sta/Elev= 30
       0 1248.73    71.9  1233.7   107.7 1224.13   133.4 1216.21     164 1204.91
   238.1 1173.44   310.9 1144.61   322.8 1140.87   382.6 1128.81   466.2  1116.4
   490.1 1107.96     502 1105.26     514 1104.44     653 1101.73   657.1 1101.68
     668 1102.81   681.9 1107.38   696.4 1114.34     768 1153.54   825.5  1181.3
   866.4 1202.21   903.3 1219.01   927.9 1229.46  1001.8 1258.38  1038.7 1274.56
    1051 1278.35  1063.3 1280.24  1087.9 1279.54  1100.2 1281.92  1136.8  1294.3
#Mann= 3 , 0 , 0
       0      .1       0     653    .045       0     668      .1       0
Bank Sta=653,668
XS Rating Curve= 0 ,0
Exp/Cntr=0.3,0.1

Type RM Length L Ch R = 1 ,17631   ,309.567,330.586,326.346
XS GIS Cut Line= 3
     1675652.097      271632.012     1675520.526      271180.153
     1675505.829      270511.125
#Sta/Elev= 30
       0 1186.87    67.8 1194.65    97.9 1196.39   126.7 1196.94   159.1 1196.52
   203.3 1190.02   251.2 1177.67   352.2 1143.33   401.6 1125.09   438.7 1112.59
   452.3 1106.19   463.1 1100.11   471.6 1097.86   475.6 1097.65   478.1 1097.73
   570.6 1099.23   625.5 1103.82     662 1104.71   677.5  1107.6     725 1121.37
   772.5 1133.93   784.4 1137.92   891.3 1180.54     915 1193.16   938.8 1201.48
   974.4  1210.5    1010 1217.17  1069.4 1222.94  1081.3 1225.07  1139.8 1246.04
#Mann= 3 , 0 , 0
       0      .1       0   463.1    .045       0   478.1      .1       0
Bank Sta=463.1,478.1
XS Rating Curve= 0 ,0
Exp/Cntr=0.3,0.1

Type RM Length L Ch R = 1 ,17300.4 ,759.944,1092.502,898.664
XS GIS Cut Line= 4
     1675675.728      271714.797     1675695.872      271400.046
     1675700.375      271147.238      1675698.39      270508.672
#Sta/Elev= 30
       0 1176.42   148.1 1171.14   193.1 1168.56   219.5 1166.55   287.5 1159.06
   356.2 1152.45   397.8 1144.96   421.6 1139.53   445.3 1132.72   504.7 1111.99
   552.2  1098.8   556.2 1098.37   571.2 1097.47   611.6 1097.86   644.7 1097.31
   694.7 1100.16   756.9 1102.45   789.7 1105.53   801.5 1108.66   837.1 1121.81
     849 1124.78   872.8 1128.76   899.8 1134.49  1015.2 1164.37  1027.1 1168.06
  1054.6 1179.83  1118.1 1211.32  1169.6 1235.02  1193.3 1244.54  1206.8 1249.01
#Mann= 3 , 0 , 0
       0      .1       0   556.2    .045       0   571.2      .1       0
Bank Sta=556.2,571.2
XS Rating Curve= 0 ,0
Exp/Cntr=0.3,0.1

Type RM Length L Ch R = 1 ,16207.9 ,565.035,576.913,590.891
XS GIS Cut Line= 3
     1676398.396      271264.074     1676091.132      270847.049
     1675762.754      270430.668
#Sta/Elev= 30
       0  1186.9    32.1 1178.09    72.1 1168.45   110.4 1156.04   152.2 1143.39
   172.2 1138.03   184.2  1135.3   213.7 1126.47   228.4 1123.11   352.4 1108.12
   390.6 1102.22   405.4 1100.31   452.4 1096.83   493.9 1095.06     520 1094.54
   523.5 1094.46     535 1095.17   553.8  1098.9   569.5 1103.24   599.1 1115.67
   689.8 1152.16   755.4 1177.92   789.3 1192.03   806.2 1199.53   886.4 1236.55
   901.5 1243.11   916.6 1247.49   992.2 1264.17  1030.4    1272  1048.3 1274.81
#Mann= 3 , 0 , 0
       0      .1       0     520    .045       0     535      .1       0
Bank Sta=520,535
XS Rating Curve= 0 ,0
Exp/Cntr=0.3,0.1

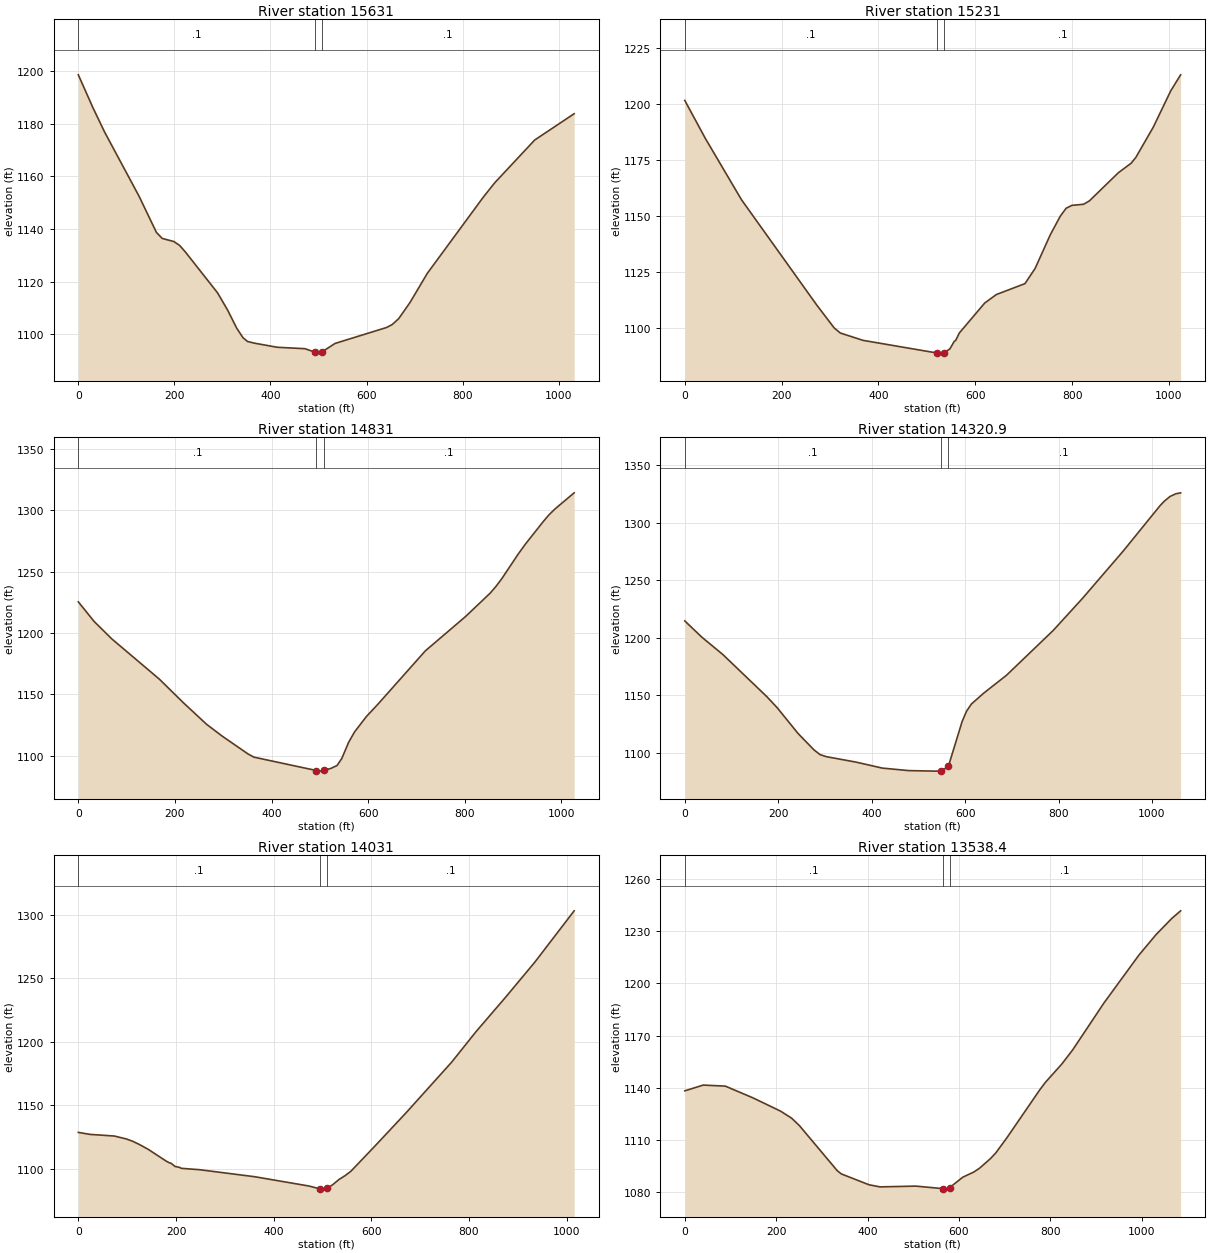
Type RM Length L Ch R = 1 ,15631   ,393.92,400,403.521
XS GIS Cut Line= 3
     1676560.854      271252.818     1676485.111      270758.658
     1676483.222      270226.282
#Sta/Elev= 30
       0  1198.6    30.5 1186.07    54.5 1176.93   126.6 1152.41   162.6 1138.71
   174.7 1136.42   198.7 1135.26   210.7 1133.81   222.7 1131.32   289.8 1115.77
   310.7 1109.24   329.9 1102.28   342.8 1098.72   352.3 1097.26   366.8 1096.62
   414.4 1095.06   471.7 1094.53   492.4 1093.22   498.1 1092.84   507.4 1093.33
   534.6 1096.53   641.4 1102.56   653.3 1103.67   666.9 1105.92   690.7 1112.12
   726.5 1123.14   843.3 1152.15     867 1157.58   950.1 1173.82  1032.3 1183.82
#Mann= 3 , 0 , 0
       0      .1       0   492.4    .045       0   507.4      .1       0
Bank Sta=492.4,507.4
XS Rating Curve= 0 ,0
Exp/Cntr=0.3,0.1

Type RM Length L Ch R = 1 ,15231   ,395.066,400,385.857
XS GIS Cut Line= 3
     1676805.237      271220.472     1676865.005      270695.196
     1676938.407      270205.133
#Sta/Elev= 30
       0 1201.67    42.3 1184.75   117.1 1157.28   272.6 1110.19   308.5 1099.98
   321.3 1097.68   368.2  1094.4   521.2 1088.74   523.6 1088.69   536.2 1088.89
   547.6 1090.59   556.5 1093.93   559.6 1094.38     567 1097.67   619.6 1111.11
   643.6 1114.89   702.7 1119.77   723.6 1126.54   754.9 1141.57   775.7 1149.95
   787.7 1153.47   799.7 1154.77   823.7 1155.25   835.7 1156.76   895.7 1169.37
     922 1173.61   931.7  1176.2   967.7 1189.72  1003.8 1205.97  1024.2 1213.13
#Mann= 3 , 0 , 0
       0      .1       0   521.2    .045       0   536.2      .1       0
Bank Sta=521.2,536.2
XS Rating Curve= 0 ,0
Exp/Cntr=0.3,0.1

Type RM Length L Ch R = 1 ,14831   ,501.61,510.032,513.759
XS GIS Cut Line= 3
     1677052.284      271289.748     1677178.353      270805.548
     1677299.387      270293.529
#Sta/Elev= 30
       0 1225.49    32.5 1209.59    69.3 1195.29   167.5 1162.58   216.6  1143.6
   265.6 1125.66   297.8 1116.07   351.5 1101.47   363.8 1098.89   492.8 1088.03
   498.7 1087.53   507.8 1088.07   523.1 1089.78   535.6 1092.11   545.4 1097.81
   559.7 1111.08   571.9 1119.49   596.3 1131.98   620.7 1142.27   718.3 1185.51
     802 1213.64   852.5 1232.53   864.7 1238.09   876.9 1244.49   910.5 1264.32
   925.7  1272.6   962.3  1290.8   974.5 1296.44   986.7 1301.14  1026.5 1314.33
#Mann= 3 , 0 , 0
       0      .1       0   492.8    .045       0   507.8      .1       0
Bank Sta=492.8,507.8
XS Rating Curve= 0 ,0
Exp/Cntr=0.3,0.1

Type RM Length L Ch R = 1 ,14320.9 ,291.851,289.968,287.666
XS GIS Cut Line= 3
     1677353.506      271331.232     1677582.871      270835.394
     1677743.245      270346.061
#Sta/Elev= 30
       0 1214.57    36.6 1200.43    81.4 1185.42   175.2    1149   197.6 1139.32
   242.3 1116.93   276.6 1102.58   289.7 1098.48   302.8 1096.75   366.2 1092.03
   422.8 1086.81   479.3 1084.63   535.9 1084.18   547.7 1084.22   551.1 1084.32
   562.7 1088.45   565.3 1089.79   593.5 1127.13   602.9 1136.09   613.6 1142.51
   640.5  1152.1   688.5 1167.37   788.5 1206.27     851 1234.03   938.4 1275.21
  1016.9 1314.45  1025.9 1318.35  1038.4 1322.55  1050.9 1324.93  1061.3 1325.77
#Mann= 3 , 0 , 0
       0      .1       0   547.7    .045       0   562.7      .1       0
Bank Sta=547.7,562.7
XS Rating Curve= 0 ,0
Exp/Cntr=0.3,0.1

Type RM Length L Ch R = 1 ,14031   ,492.013,492.523,491.77
XS GIS Cut Line= 3
     1677696.524      271423.563     1677847.589      270944.432
     1677954.627      270442.889
#Sta/Elev= 30
       0 1128.86    23.9 1127.29    73.7    1126    98.6 1123.67   111.1  1121.9
   124.8 1119.39     143 1115.57   179.4 1106.41   185.8 1105.04   189.1 1104.77
   198.2 1102.09     208 1101.29   210.7 1100.62     248 1099.55   361.2 1094.02
   472.1 1086.73   494.9 1084.47     497 1084.28   509.9 1084.89   521.4 1087.94
   533.5  1091.8   545.7 1094.75   557.8 1098.22   606.4 1117.75   671.5 1144.44
   764.2 1183.95   814.6 1208.15   873.5 1234.44   934.2 1262.37  1015.2 1302.92
#Mann= 3 , 0 , 0
       0      .1       0   494.9    .045       0   509.9      .1       0
Bank Sta=494.9,509.9
XS Rating Curve= 0 ,0
Exp/Cntr=0.3,0.1

Type RM Length L Ch R = 1 ,13538.4 ,695.372,707.477,704.752
XS GIS Cut Line= 3
     1678070.353      271523.428     1678178.627      270961.913
     1678264.239      270455.793
#Sta/Elev= 30
       0 1138.29    40.3  1141.6    88.7    1141   149.1 1134.27   209.6 1126.64
   233.8 1122.61   251.1 1118.26   333.6 1092.48   342.6  1090.6   403.1 1084.38
   427.2 1083.16   505.8  1083.6   564.9 1082.15   571.9 1081.87   579.9 1082.79
   608.5 1088.73   632.5 1091.68   644.6 1093.78   668.7 1099.31   680.7 1102.67
   704.8 1111.29     777  1138.9   789.1 1143.13   825.2 1153.69   849.3 1161.93
   916.8 1188.51   993.8 1216.18  1031.1 1227.88    1066  1237.3  1085.2 1241.63
#Mann= 3 , 0 , 0
       0      .1       0   564.9    .045       0   579.9      .1       0
Bank Sta=564.9,579.9
XS Rating Curve= 0 ,0
Exp/Cntr=0.3,0.1

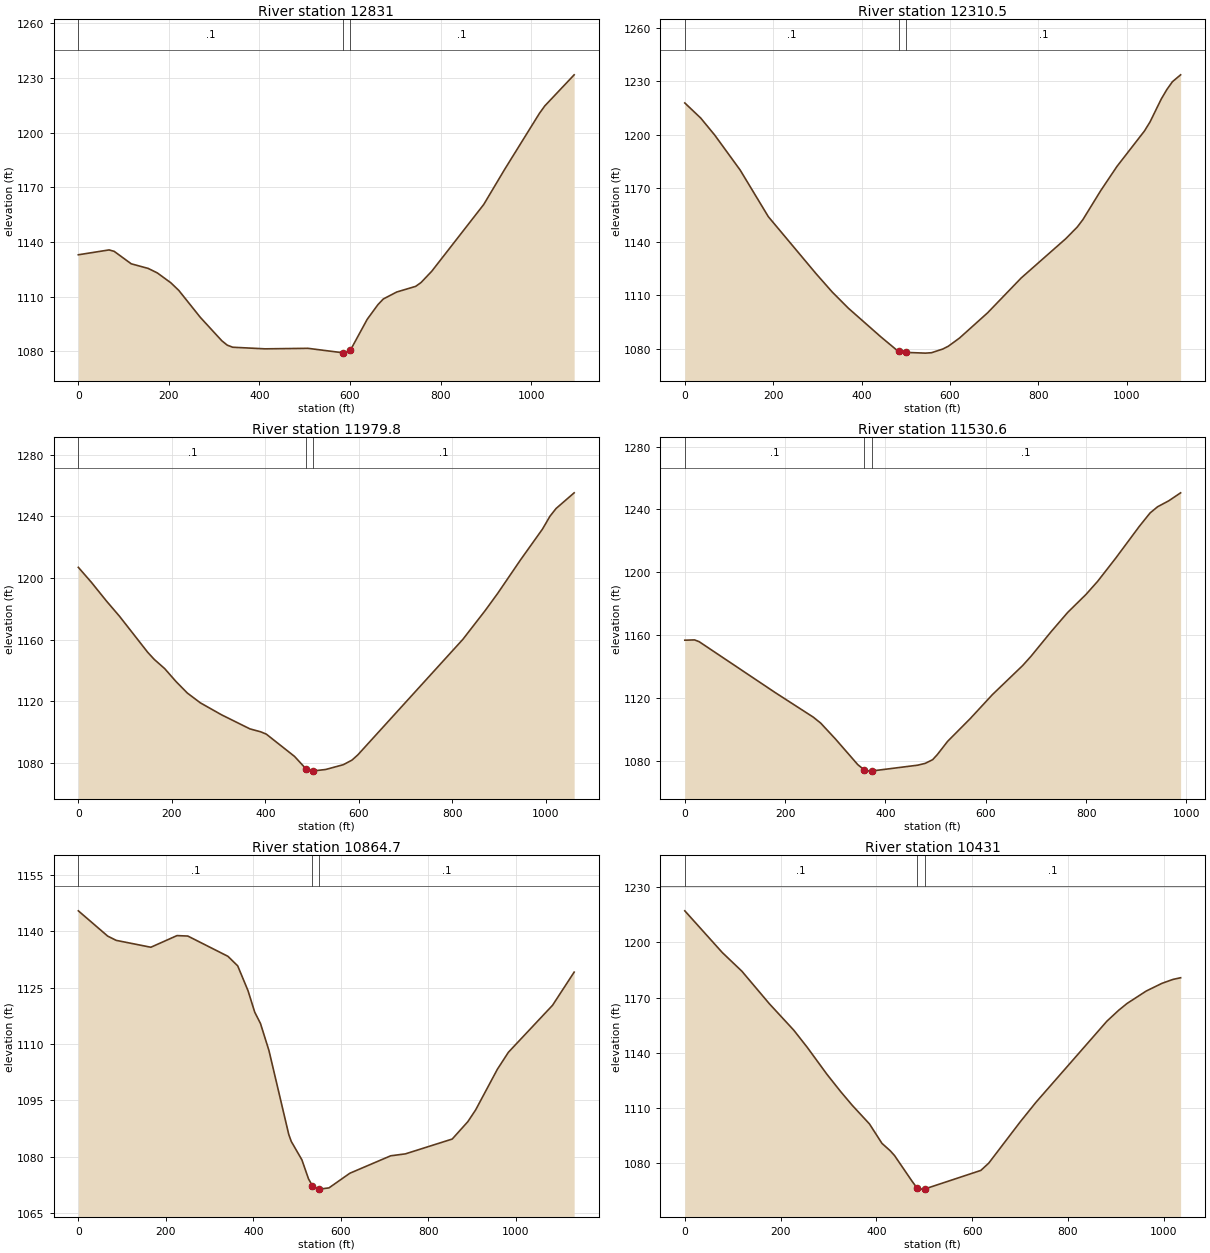
Type RM Length L Ch R = 1 ,12831   ,531.572,520.453,506.135
XS GIS Cut Line= 3
     1678560.421      271479.981     1678587.329      270888.966
     1678614.817      270386.321
#Sta/Elev= 30
       0 1132.99    67.9 1135.66    79.2 1134.87   116.8 1128.05   154.2 1125.52
   174.4 1123.06   204.3 1117.64   221.9 1113.45   269.5 1098.66     317 1085.83
   328.9 1083.45   340.9 1082.31   412.1 1081.43   507.2 1081.71   584.1 1079.28
     590 1079.08   599.1 1080.73   602.3 1081.34   637.9 1097.59   661.7 1105.68
   673.6 1108.77   703.2 1112.59     745 1115.68   756.8 1117.77   780.6 1123.99
   895.2 1160.53   942.1 1180.05  1018.4 1210.55  1030.3 1214.64    1095 1231.64
#Mann= 3 , 0 , 0
       0      .1       0   584.1    .045       0   599.1      .1       0
Bank Sta=584.1,599.1
XS Rating Curve= 0 ,0
Exp/Cntr=0.3,0.1

Type RM Length L Ch R = 1 ,12310.5 ,326.925,330.691,333.13
XS GIS Cut Line= 3
     1679093.418      271458.096     1678913.885      270999.683
     1678692.313      270409.808
#Sta/Elev= 30
       0 1217.92    36.1 1209.42    67.8 1199.86   125.4 1180.21   189.1 1154.07
   297.1 1122.07   333.8 1111.74   370.4 1102.64   443.7 1086.61   480.4 1079.04
   485.6 1078.55   500.6 1077.85   544.8 1077.45   558.5 1077.68   583.9 1079.74
   596.6 1081.34   621.9 1085.92   685.4 1100.07   761.4 1119.62   862.9 1141.81
   888.3 1148.22     901 1152.35   941.3  1168.6   978.2 1182.25  1040.5 1202.17
  1053.1 1207.24  1078.5 1220.09  1091.2 1225.45  1103.9 1229.86  1122.4 1233.71
#Mann= 3 , 0 , 0
       0      .1       0   485.6    .045       0   500.6      .1       0
Bank Sta=485.6,500.6
XS Rating Curve= 0 ,0
Exp/Cntr=0.3,0.1

Type RM Length L Ch R = 1 ,11979.8 ,460.673,449.192,438.149
XS GIS Cut Line= 3
     1679259.296      271404.436     1679169.021      270902.792
     1679003.449      270377.826
#Sta/Elev= 30
       0 1206.97    27.9 1197.26    60.1 1185.13    88.2 1175.17   148.5 1151.79
   162.4 1147.23   184.7 1141.25   208.8 1132.91     233 1125.45     261 1119.05
   306.3 1111.29   366.8 1102.19   389.8 1100.28   401.9 1098.78   462.2 1084.34
   487.2 1076.13   498.4 1074.77   502.2  1074.9   528.9 1075.83   566.7 1078.95
   585.1 1081.91   597.6  1085.3   822.3 1160.28   869.6 1178.79   896.4 1189.95
   945.3 1211.71   992.6 1231.84  1008.4 1240.08  1021.5 1245.13  1060.2  1255.3
#Mann= 3 , 0 , 0
       0      .1       0   487.2    .045       0   502.2      .1       0
Bank Sta=487.2,502.2
XS Rating Curve= 0 ,0
Exp/Cntr=0.3,0.1

Type RM Length L Ch R = 1 ,11530.6 ,667.948,665.947,611.825
XS GIS Cut Line= 3
     1679656.697      271143.209     1679430.032       270838.65
     1679060.102      270355.051
#Sta/Elev= 30
       0 1156.96    19.4 1157.14    28.4 1156.06   179.8 1123.77   256.2 1108.06
     271 1104.26     300 1094.32     345 1077.85   357.7 1074.62   367.8 1073.77
   372.7 1073.86   464.2 1077.54   479.2 1078.69   494.1 1081.03   503.4 1084.25
     524  1092.7   568.8 1107.05   613.2 1122.36   673.5 1140.82   689.7 1146.55
   730.4  1162.4   763.2 1174.55   799.8 1186.02     823 1194.32   859.1 1209.09
   906.3 1229.34   927.6 1237.79   942.5 1241.72   964.9 1245.53   988.5 1250.59
#Mann= 3 , 0 , 0
       0      .1       0   357.7    .045       0   372.7      .1       0
Bank Sta=357.7,372.7
XS Rating Curve= 0 ,0
Exp/Cntr=0.3,0.1

Type RM Length L Ch R = 1 ,10864.7 ,442.348,433.717,432.111
XS GIS Cut Line= 4
     1679704.539      271130.619     1679913.533      270785.652
      1679830.88      270678.417     1679435.112      270234.209
#Sta/Elev= 30
       0 1145.44    67.1 1138.71    86.7 1137.57   165.8 1135.74   225.6 1138.84
   250.4 1138.72   342.1 1133.32   364.4 1130.78   387.9  1124.2   403.3 1118.46
   416.5 1115.42   435.9 1108.21   481.2 1085.85   486.9 1084.01   511.2 1079.11
   526.2 1074.08   535.3 1072.17   550.3 1071.32   551.4 1071.31   573.1 1071.64
   620.8 1075.54   714.3 1080.19   747.8  1080.7   854.9 1084.65   890.6 1089.28
   908.4  1092.4   958.1 1103.23   983.4 1107.77  1084.3 1120.28  1133.7 1129.11
#Mann= 3 , 0 , 0
       0      .1       0   535.3    .045       0   550.3      .1       0
Bank Sta=535.3,550.3
XS Rating Curve= 0 ,0
Exp/Cntr=0.3,0.1

Type RM Length L Ch R = 1 ,10431   ,389.619,400,405.673
XS GIS Cut Line= 3
     1680602.955      270682.556     1680173.768      270439.557
     1679782.435      270064.789
#Sta/Elev= 30
       0 1217.18    78.3 1194.51   119.3 1184.34   176.4 1166.74   227.5 1152.34
   255.7 1142.99   296.6 1128.42   325.5 1118.94   349.6 1111.52   385.5 1101.41
   411.6 1090.85   429.1 1086.77   437.8 1084.24     474 1070.45   481.3 1067.84
   485.7 1066.87     490 1066.07   493.2    1066   500.7 1066.07     618 1076.17
   634.5 1080.13   699.9 1102.45   733.1 1113.19   881.1 1157.23   905.9 1163.21
   923.1 1166.84   963.2 1173.61   996.1  1177.8  1019.2 1179.94    1035 1180.82
#Mann= 3 , 0 , 0
       0      .1       0   485.7    .045       0   500.7      .1       0
Bank Sta=485.7,500.7
XS Rating Curve= 0 ,0
Exp/Cntr=0.3,0.1

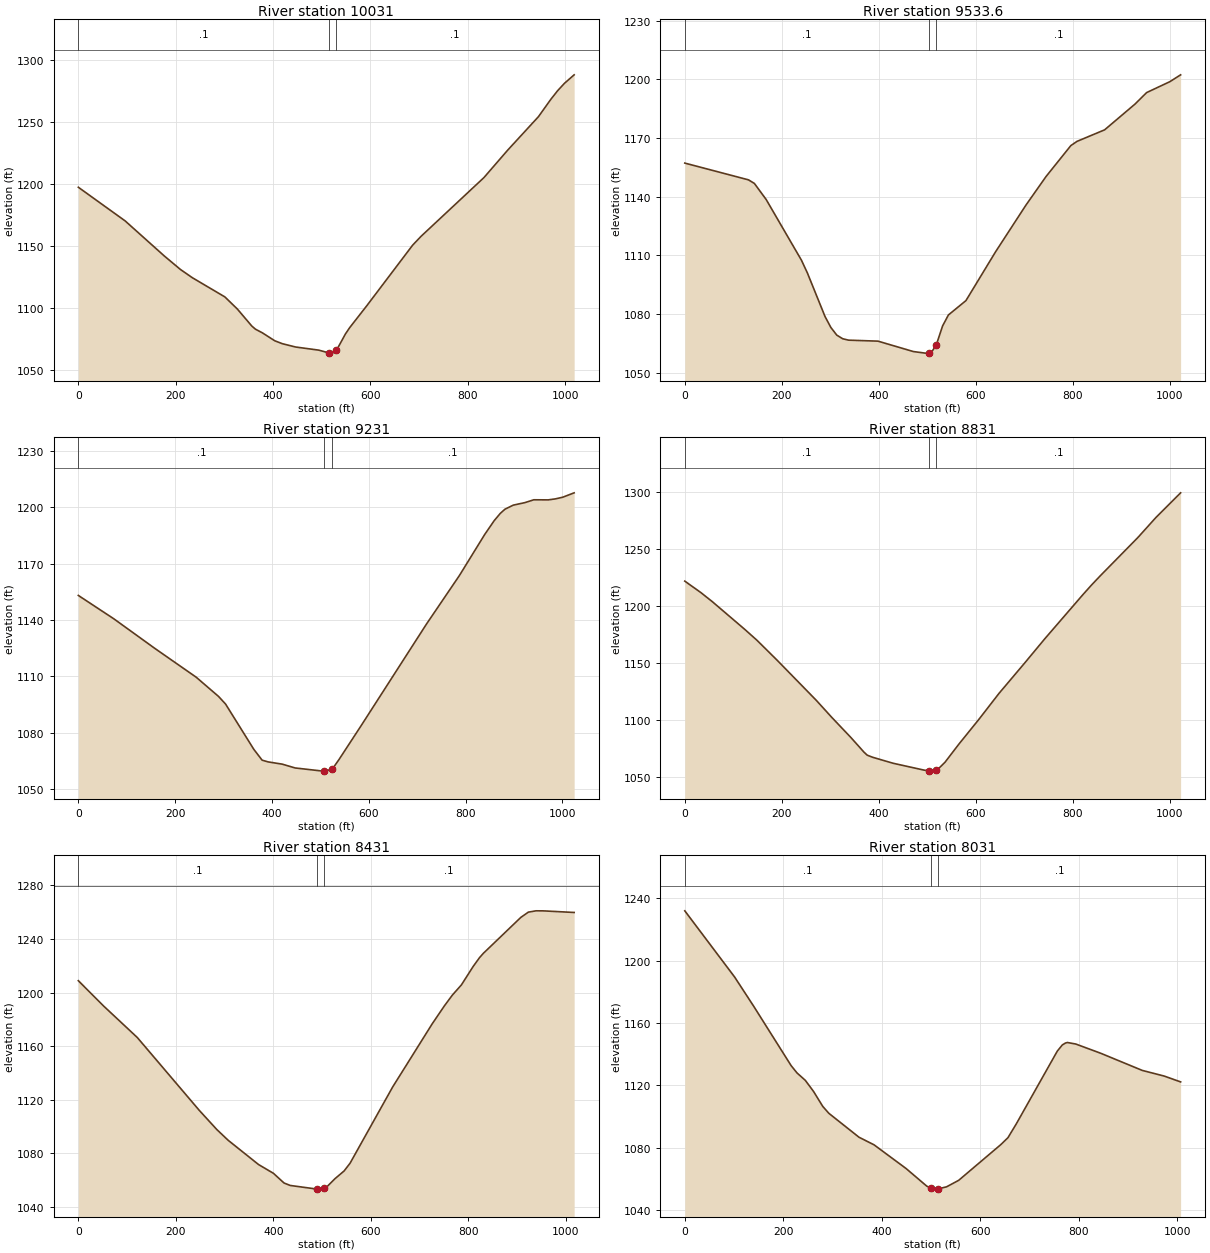
Type RM Length L Ch R = 1 ,10031   ,488.356,497.366,504.281
XS GIS Cut Line= 3
     1680701.272      270560.661     1680405.137      270130.857
     1680141.876      269709.876
#Sta/Elev= 30
       0 1197.33    96.2 1170.21   176.5    1142   209.7 1131.11   234.2 1124.45
     301 1108.99   326.7 1099.21   356.2 1085.58   363.9 1082.97   377.9 1080.08
   403.5 1073.65     419  1071.3   446.2 1068.64   493.7 1066.12   514.4 1063.91
   521.9  1063.7   529.4 1066.09   531.6 1066.91   548.8 1079.24   557.5 1084.27
   592.5 1101.86   686.7 1150.66   703.9 1157.76   833.2 1205.13     882 1227.23
   945.2  1254.2   970.6 1268.17   984.6 1275.13   998.6 1281.07  1018.5  1287.9
#Mann= 3 , 0 , 0
       0      .1       0   514.4    .045       0   529.4      .1       0
Bank Sta=514.4,529.4
XS Rating Curve= 0 ,0
Exp/Cntr=0.3,0.1

Type RM Length L Ch R = 1 ,9533.6  ,311.117,302.634,289.518
XS GIS Cut Line= 3
     1680934.932      270448.709     1680830.319       269956.93
     1680750.609      269443.696
#Sta/Elev= 30
       0 1157.17   131.3  1148.6   143.4 1146.78   167.7 1138.58   240.5 1107.53
   252.6  1101.1   289.1 1078.75   301.2 1073.13   313.3 1069.25   325.5 1067.39
   337.6 1066.67   398.3 1066.16   471.1 1060.85   495.6 1060.04   503.2 1060.12
   507.5 1060.16   518.2 1064.03   531.5 1073.95   543.5 1079.55   579.6 1086.88
   640.9 1111.91   703.3 1135.69   744.9 1150.35   795.9 1166.11   808.6 1168.27
   865.5 1174.16     928 1187.29   952.1  1193.2  1000.1 1198.79  1022.2 1202.28
#Mann= 3 , 0 , 0
       0      .1       0   503.2    .045       0   518.2      .1       0
Bank Sta=503.2,518.2
XS Rating Curve= 0 ,0
Exp/Cntr=0.3,0.1

Type RM Length L Ch R = 1 ,9231    ,406.462,400,401.49
XS GIS Cut Line= 3
     1681374.963      270259.047     1681074.867      269839.665
     1680766.896      269434.171
#Sta/Elev= 30
       0  1153.1    73.2 1140.69   158.2  1124.9   243.4 1109.62   289.6 1099.39
   304.2  1095.3   362.5 1071.23   379.6 1065.49   391.8 1064.58     421 1063.38
   447.7 1061.35   505.3 1059.66   508.2 1059.68   523.2 1060.61   525.3    1061
   538.3 1065.79   584.2 1083.87   719.1 1137.88   786.9 1163.61   839.4 1185.53
     859 1192.89   871.6 1196.75   881.2 1198.96   898.3 1201.12   922.5 1202.47
   940.8 1203.97   970.6 1203.92   985.5 1204.46  1000.5 1205.33  1024.1 1207.67
#Mann= 3 , 0 , 0
       0      .1       0   508.2    .045       0   523.2      .1       0
Bank Sta=508.2,523.2
XS Rating Curve= 0 ,0
Exp/Cntr=0.3,0.1

Type RM Length L Ch R = 1 ,8831    ,406.251,400,391.57
XS GIS Cut Line= 3
     1681694.019      270012.793     1681355.107      269630.305
     1681089.992      269192.664
#Sta/Elev= 30
       0 1221.85    33.3 1211.75    56.7 1203.85   123.9 1179.44   149.2 1169.82
   190.5 1152.43   271.2 1117.26   302.9 1102.42   342.6 1084.63   369.5 1071.84
   376.3 1069.13   387.4 1067.31   429.8 1062.03   493.3 1056.04   503.5 1055.45
   509.2 1055.14   518.5 1056.52   523.3  1057.3   536.8 1062.98   564.9  1078.6
   606.6 1100.56   648.2 1123.41     701 1149.97   742.3 1171.14     822  1210.4
   839.3 1218.59   856.4 1226.27   934.4 1260.04   971.5 1277.56  1022.7 1299.32
#Mann= 3 , 0 , 0
       0      .1       0   503.5    .045       0   518.5      .1       0
Bank Sta=503.5,518.5
XS Rating Curve= 0 ,0
Exp/Cntr=0.3,0.1

Type RM Length L Ch R = 1 ,8431    ,392.992,400,397.574
XS GIS Cut Line= 3
     1682062.727      269695.841     1681646.132      269424.531
      1681312.39      269025.402
#Sta/Elev= 30
       0 1208.86    52.2 1189.86     121 1166.47     248  1112.2     284 1097.88
   307.4 1089.82   369.8  1071.7   400.3 1065.17   422.1 1057.93   434.9 1056.09
   489.7 1053.38   491.6 1053.36   504.7    1054   508.4 1054.51   526.9 1061.23
   545.4 1066.93   557.5 1072.64   644.9 1129.51     726  1176.6   751.3 1190.16
   767.5 1198.11     786  1205.7   810.3 1219.54     823 1225.94   830.7 1229.13
     908 1256.09   923.5 1260.01     939 1260.98   953.6 1260.96  1017.4 1259.75
#Mann= 3 , 0 , 0
       0      .1       0   489.7    .045       0   504.7      .1       0
Bank Sta=489.7,504.7
XS Rating Curve= 0 ,0
Exp/Cntr=0.3,0.1

Type RM Length L Ch R = 1 ,8031    ,784.077,800,821.635
XS GIS Cut Line= 3
     1682243.156      269537.963     1681922.728      269144.265
     1681567.206       268792.87
#Sta/Elev= 30
       0 1231.86   101.2  1189.4   139.4 1170.92   215.9  1132.6   227.8 1127.92
   244.7 1123.15   261.3  1116.1   280.1 1106.47   292.4 1102.04   353.7 1086.68
   384.3  1081.8   449.4 1066.59   491.4 1055.29   500.1 1054.14   505.8 1053.39
   515.1 1053.58   531.5 1054.87   556.1 1059.02   641.8 1081.97   656.2 1086.39
   672.9 1095.11   756.4  1141.9   766.6 1145.86   773.1 1147.09   776.9 1147.41
   793.8 1146.45   844.5 1140.53   928.9 1129.52   973.4  1125.9  1006.8 1122.15
#Mann= 3 , 0 , 0
       0      .1       0   500.1    .045       0   515.1      .1       0
Bank Sta=500.1,515.1
XS Rating Curve= 0 ,0
Exp/Cntr=0.3,0.1

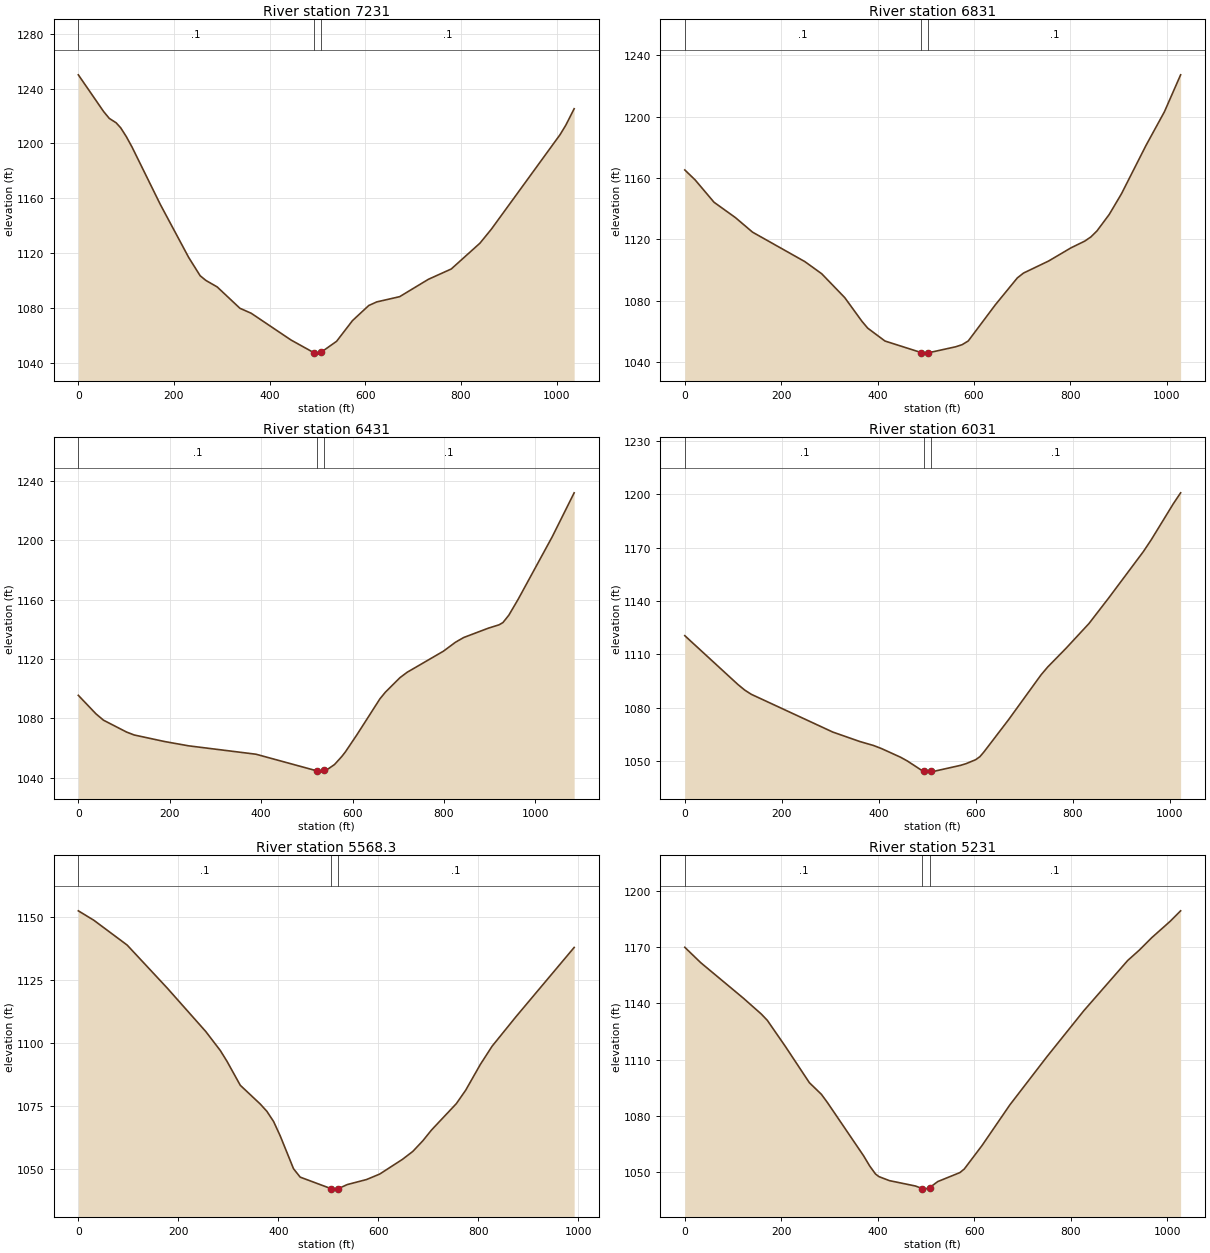
Type RM Length L Ch R = 1 ,7231    ,402.065,400,388.639
XS GIS Cut Line= 3
     1682495.846      269387.851     1682498.139      268887.656
     1682572.243      268356.072
#Sta/Elev= 30
       0 1250.08      53 1223.24    64.8 1218.28    79.1 1215.08    88.6 1211.42
   100.4 1204.98   112.3  1197.4   171.7 1155.35     231 1116.74   254.8 1103.51
   266.7 1100.11   290.4 1095.36   337.9  1079.8   361.6 1076.14   444.8 1056.63
   492.7 1047.37   504.2 1047.07   507.7 1047.72   540.1  1055.7   573.4 1070.81
   607.4 1081.81     624 1084.42     672 1088.26   731.9 1100.89   779.9 1108.45
   839.8 1127.24   863.8  1137.5  1007.6 1206.52  1019.6 1213.45  1036.9 1225.34
#Mann= 3 , 0 , 0
       0      .1       0   492.7    .045       0   507.7      .1       0
Bank Sta=492.7,507.7
XS Rating Curve= 0 ,0
Exp/Cntr=0.3,0.1

Type RM Length L Ch R = 1 ,6831    ,417.177,400,390.735
XS GIS Cut Line= 3
      1682924.12       269332.42     1682872.271      268837.464
     1682681.936      268341.776
#Sta/Elev= 30
       0 1165.21    21.4 1158.73    60.6 1144.17     105 1134.16   140.6 1124.66
     249  1105.5     284 1097.59   331.8 1082.04   367.6 1066.56   379.5 1062.13
   415.3 1053.75   490.2 1046.26     499 1045.87   505.2 1046.07   561.8 1049.99
   575.3 1051.37     588 1053.79   644.5 1077.46   689.7 1094.81   702.5    1098
   754.8 1105.88   800.8  1114.4   829.6 1118.83   842.4 1121.56   855.1 1125.49
   880.5 1136.22   905.9 1149.68   956.8 1181.19     995 1203.11  1028.6 1227.17
#Mann= 3 , 0 , 0
       0      .1       0   490.2    .045       0   505.2      .1       0
Bank Sta=490.2,505.2
XS Rating Curve= 0 ,0
Exp/Cntr=0.3,0.1

Type RM Length L Ch R = 1 ,6431    ,395.438,400,396.735
XS GIS Cut Line= 3
     1683494.886       269112.43     1683117.239      268740.194
     1682748.809       268325.56
#Sta/Elev= 30
       0 1095.59    38.7 1083.08    55.2 1078.81   105.4 1070.86   122.1 1068.87
   188.7 1064.45   241.2 1061.56   388.8 1055.89   522.8 1044.61   525.4  1044.5
   537.8 1044.94   544.7 1045.58   560.6 1048.96   576.5 1054.36   584.3 1057.44
   609.5 1068.99     660 1093.27   671.8  1097.7   703.5 1107.43   719.4 1111.12
   798.8 1125.34   825.4 1131.42   843.3 1134.58   896.9 1140.84   920.7 1143.14
   929.1 1144.65   941.8 1149.54   962.7 1160.51  1037.1 1202.58  1084.9  1232.1
#Mann= 3 , 0 , 0
       0      .1       0   522.8    .045       0   537.8      .1       0
Bank Sta=522.8,537.8
XS Rating Curve= 0 ,0
Exp/Cntr=0.3,0.1

Type RM Length L Ch R = 1 ,6031    ,460.653,462.697,470.931
XS GIS Cut Line= 3
     1683717.205      268976.747     1683452.959      268551.804
     1683107.878      268160.111
#Sta/Elev= 30
       0 1120.49   109.5 1093.05   123.5 1089.92   136.9 1087.55   305.3 1066.28
   361.2 1060.95   389.1 1058.75   405.8 1056.99   445.1 1052.12   459.1    1050
     487 1045.03   492.9 1044.67   500.4 1044.33   507.9 1044.35   516.9 1044.42
   568.5 1047.57   580.2 1048.55   599.9 1050.78   608.4 1052.43   616.8 1055.11
   667.2 1073.09   734.5 1098.42   748.1 1102.81   785.9 1113.34   833.4 1127.31
   873.8 1141.58   945.6 1167.78   961.7 1174.36  1007.4  1194.7  1022.4 1200.81
#Mann= 3 , 0 , 0
       0      .1       0   492.9    .045       0   507.9      .1       0
Bank Sta=492.9,507.9
XS Rating Curve= 0 ,0
Exp/Cntr=0.3,0.1

Type RM Length L Ch R = 1 ,5568.3  ,333.758,337.303,338.982
XS GIS Cut Line= 3
     1684019.357      268757.181     1683793.755      268310.994
     1683577.233      267869.801
#Sta/Elev= 30
       0 1152.65    31.1 1148.89    97.7 1139.02   177.5 1121.99   254.8 1104.66
   283.9 1097.09   297.2 1092.83   323.8 1083.28   363.7 1075.83     377 1072.92
   390.4 1068.88   403.7 1063.14   430.3 1050.08   443.6 1046.75   504.8 1042.21
     510 1041.98   519.8 1042.18   537.7 1043.79   576.2 1045.79   602.6 1047.97
   648.1 1053.82   668.7 1056.96   688.7 1061.18   706.3 1065.51   755.8 1075.97
   774.5 1081.31   803.9 1091.59   827.4 1098.83   874.8 1110.48   991.4 1138.08
#Mann= 3 , 0 , 0
       0      .1       0   504.8    .045       0   519.8      .1       0
Bank Sta=504.8,519.8
XS Rating Curve= 0 ,0
Exp/Cntr=0.3,0.1

Type RM Length L Ch R = 1 ,5231    ,393.26,400,400.299
XS GIS Cut Line= 3
     1684201.171      268642.921     1684049.917      268166.871
     1683855.662      267676.268
#Sta/Elev= 30
       0 1169.93    33.3 1161.65     121 1142.84   158.4 1134.31   170.9 1130.95
   208.3 1117.02   258.1 1097.64     283 1091.43   295.5 1087.04   370.2 1058.69
   383.1 1053.15   395.1  1048.9     402 1047.52   423.8 1045.35   477.7 1042.48
     492 1041.13   496.6 1040.81     507 1041.58   524.1 1044.85   569.9 1049.64
     579 1051.55   615.6 1064.03   673.4 1085.78     750 1111.44   826.7 1136.08
   917.5 1162.87   941.6 1168.42   967.1    1175  1005.4 1183.77  1027.2  1189.4
#Mann= 3 , 0 , 0
       0      .1       0     492    .045       0     507      .1       0
Bank Sta=492,507
XS Rating Curve= 0 ,0
Exp/Cntr=0.3,0.1