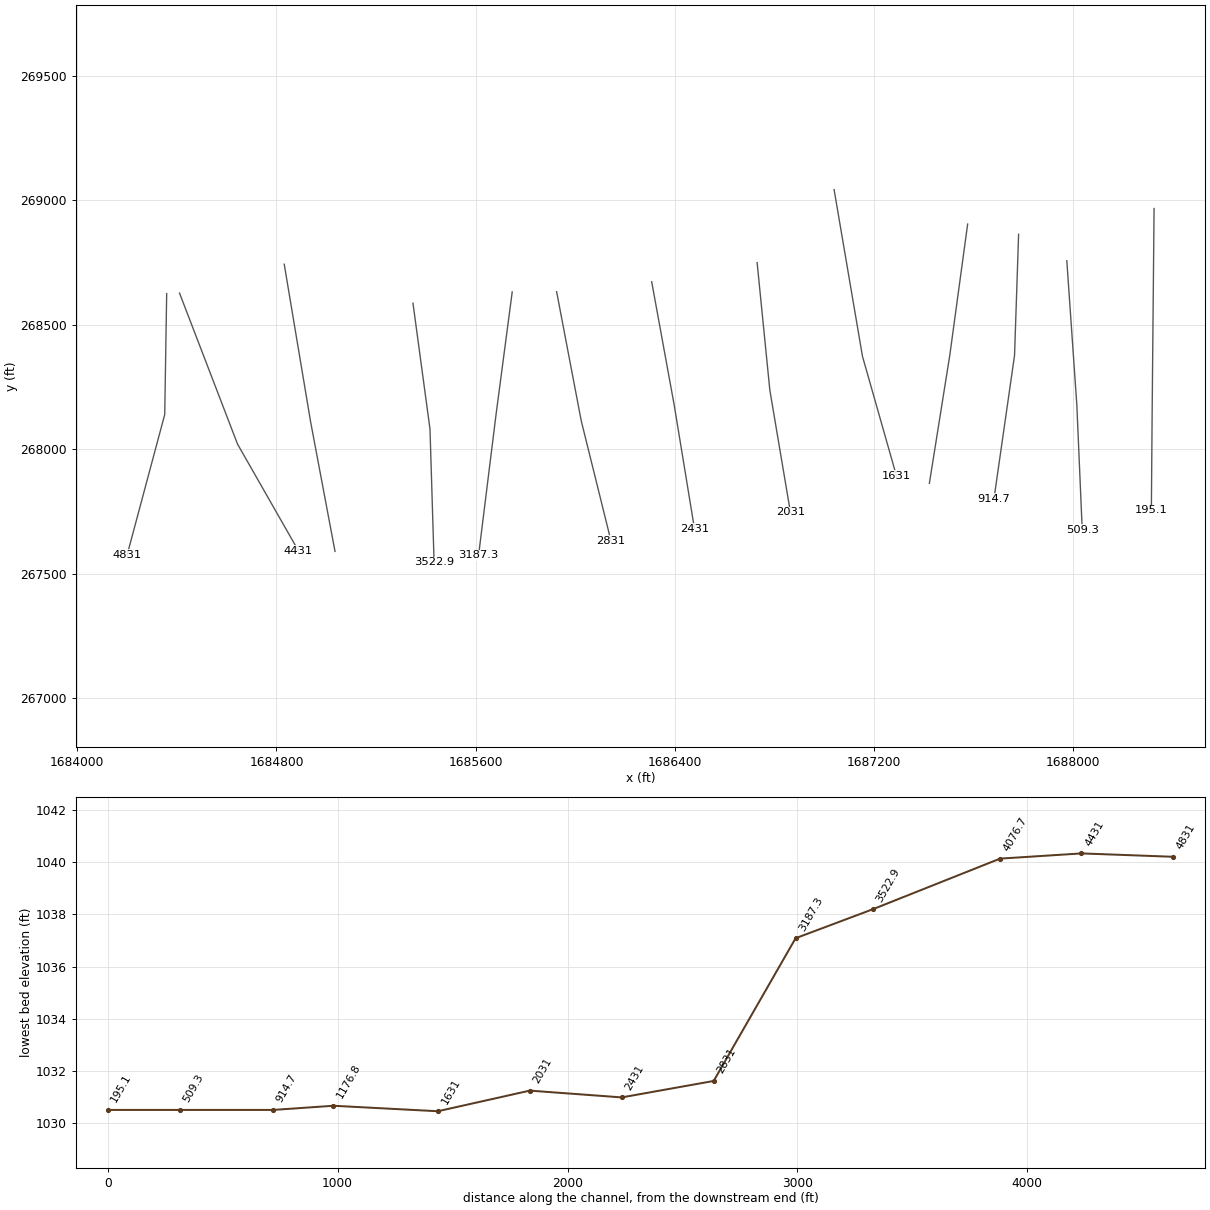
HEC-RAS study CoburnFk.prj: CoburnFk

--- CoburnFk.g01 (geometry) --- (continued)

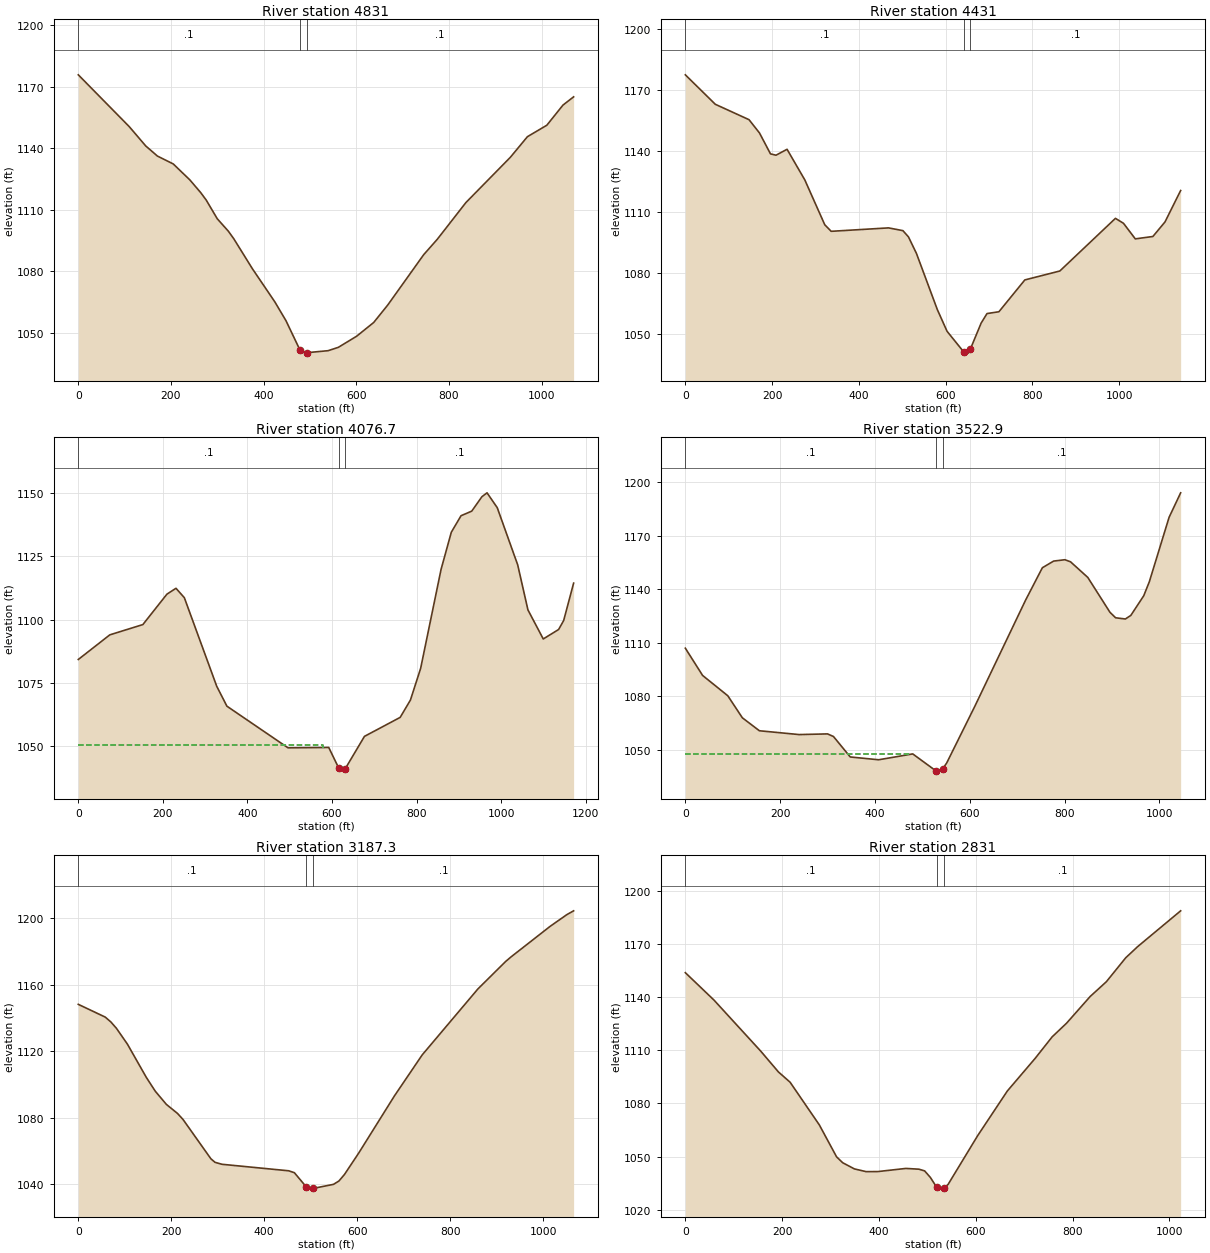
Type RM Length L Ch R = 1 ,4831    ,391.546,400,417.887
XS GIS Cut Line= 3
     1684359.103      268625.672     1684351.276      268140.072
     1684200.336      267576.353
#Sta/Elev= 30
       0 1175.84     110 1150.59   145.6 1141.17   170.8 1136.25     205  1132.4
   240.6 1124.68   264.4 1118.39   276.2 1114.78     300 1105.68   323.7 1099.69
   335.6 1095.96     376 1081.27   424.2 1065.21   448.4 1055.97   478.2 1041.86
   490.1 1040.21   493.2 1040.42   539.3  1041.4   561.4 1043.04   600.7 1048.43
   637.6 1055.13   668.1 1063.69   745.6  1088.2   774.7 1095.63   836.7 1113.59
   932.6 1135.64   969.5 1145.69  1011.4 1151.28  1046.2 1161.08  1069.2 1165.11
#Mann= 3 , 0 , 0
       0      .1       0   478.2    .045       0   493.2      .1       0
Bank Sta=478.2,493.2
XS Rating Curve= 0 ,0
Exp/Cntr=0.3,0.1

Type RM Length L Ch R = 1 ,4431    ,358.875,354.283,346.1
XS GIS Cut Line= 3
     1684410.693      268627.721     1684643.648      268021.271
     1684887.667      267593.863
#Sta/Elev= 30
       0  1177.4    69.1 1162.89   146.8 1155.31   170.9 1148.78   196.3 1138.47
   209.1 1137.82   234.5 1140.73   275.5 1125.62   321.4 1103.57   336.2 1100.33
   468.4 1102.02   501.6 1100.66   514.4 1097.57   532.8 1089.42   580.8 1061.84
   603.3  1051.1   642.2 1040.81   652.1 1040.34   657.2 1042.39   681.9 1055.13
   695.4 1059.82   722.9 1060.72   782.6 1076.39   863.3 1080.79   991.5 1106.72
    1010 1104.28  1037.3 1096.61  1077.8 1097.78  1105.7 1104.94  1141.8 1120.42
#Mann= 3 , 0 , 0
       0      .1       0   642.2    .045       0   657.2      .1       0
Bank Sta=642.2,657.2
XS Rating Curve= 0 ,0
Exp/Cntr=0.3,0.1

Type RM Length L Ch R = 1 ,4076.7  ,557.634,553.746,549.74
XS GIS Cut Line= 3
       1684831.2      268743.549     1684936.959      268111.831
     1685035.159      267590.302
#Sta/Elev= 30
       0 1084.22    74.5 1093.94   152.7    1098   209.5    1110     231 1112.32
   250.7 1108.62   327.3 1073.65   351.4 1065.78   495.9 1049.34   592.2 1049.48
   616.2  1041.2   628.3 1040.14   631.2 1041.08   676.6 1053.86   761.1 1061.36
   785.3 1068.19   809.5 1080.72   857.8  1119.8     882 1134.45     905 1140.97
   930.3 1142.78   954.4 1148.48   966.5 1150.01   990.7 1144.12    1039 1121.56
  1063.2 1103.79  1099.4 1092.32  1135.7 1096.05  1147.7  1099.6  1171.2 1114.36
#Mann= 3 , 0 , 0
       0      .1       0   616.2    .045       0   631.2      .1       0
#XS Ineff= 2 , 0
          578.21 1050.36
Permanent Ineff=
       F       F
Bank Sta=616.2,631.2
XS Rating Curve= 0 ,0
Exp/Cntr=0.3,0.1

Type RM Length L Ch R = 1 ,3522.9  ,338.957,335.645,330.58
XS GIS Cut Line= 3
     1685348.217      268587.365     1685416.591      268081.723
     1685433.031      267547.416
#Sta/Elev= 30
       0 1107.02    36.4 1091.76    89.5 1080.41   120.3 1068.05   156.2  1060.8
   240.1 1058.66     300 1059.04   312.5 1057.57   347.9 1046.12   407.8 1044.56
   479.7 1047.83     528 1038.47   539.3  1038.2     543 1039.61   551.2  1042.7
   610.6 1074.47   717.5 1133.79   753.1 1152.04   776.9 1155.78   800.7 1156.53
   812.5 1155.37   848.9 1146.64   895.7 1127.11   907.6 1124.04   928.2 1123.36
   939.7 1125.36     967 1136.39   978.8 1144.26  1020.4 1180.25  1044.8 1193.98
#Mann= 3 , 0 , 0
       0      .1       0     528    .045       0     543      .1       0
#XS Ineff= 2 , 0
          477.24 1047.87
Permanent Ineff=
       F       F
Bank Sta=528,543
XS Rating Curve= 0 ,0
Exp/Cntr=0.3,0.1

Type RM Length L Ch R = 1 ,3187.3  ,349.18,356.326,364.543
XS GIS Cut Line= 3
     1685746.797      268632.351     1685682.079      268141.675
     1685611.783      267575.194
#Sta/Elev= 30
       0 1148.26    57.8 1140.61    69.8 1137.74    81.8 1133.94   105.7 1124.31
   146.2 1104.39   165.6 1096.01   189.5 1088.07   213.5 1082.62   225.5 1078.94
   285.3 1055.34   294.3  1053.2   309.3 1052.03   452.9 1048.11     465 1046.96
     490  1038.6   500.9 1037.09     505  1037.5     549 1039.95   560.7 1041.95
   572.7 1045.89   603.6 1058.89   680.3  1093.2   740.1 1117.88   859.8 1157.51
   919.6 1174.06   931.4 1176.86  1015.3 1195.19  1051.2 1202.22  1065.8 1204.52
#Mann= 3 , 0 , 0
       0      .1       0     490    .045       0     505      .1       0
Bank Sta=490,505
XS Rating Curve= 0 ,0
Exp/Cntr=0.3,0.1

Type RM Length L Ch R = 1 ,2831    ,400.478,400,397.886
XS GIS Cut Line= 3
     1685925.146      268633.335     1686023.945      268114.989
     1686143.139      267633.829
#Sta/Elev= 30
       0 1153.79    59.3 1138.29     156 1109.44   192.3 1097.78   216.5 1091.95
   276.9 1067.85   312.5 1049.84   325.2  1046.5   349.4 1043.03   373.6 1041.49
   397.8 1041.53   455.7  1043.3   482.4 1042.88   494.4 1041.92   506.3 1038.21
   518.6 1032.99   520.2  1032.9   530.7 1031.62   535.2 1032.42     543 1034.33
   604.1 1061.84   665.3    1087   722.9 1105.46   757.9 1117.56   787.6 1125.25
   836.5 1140.36   869.9 1148.68   909.9 1162.19   934.4 1168.46  1023.4  1188.7
#Mann= 3 , 0 , 0
       0      .1       0   520.2    .045       0   535.2      .1       0
Bank Sta=520.2,535.2
XS Rating Curve= 0 ,0
Exp/Cntr=0.3,0.1

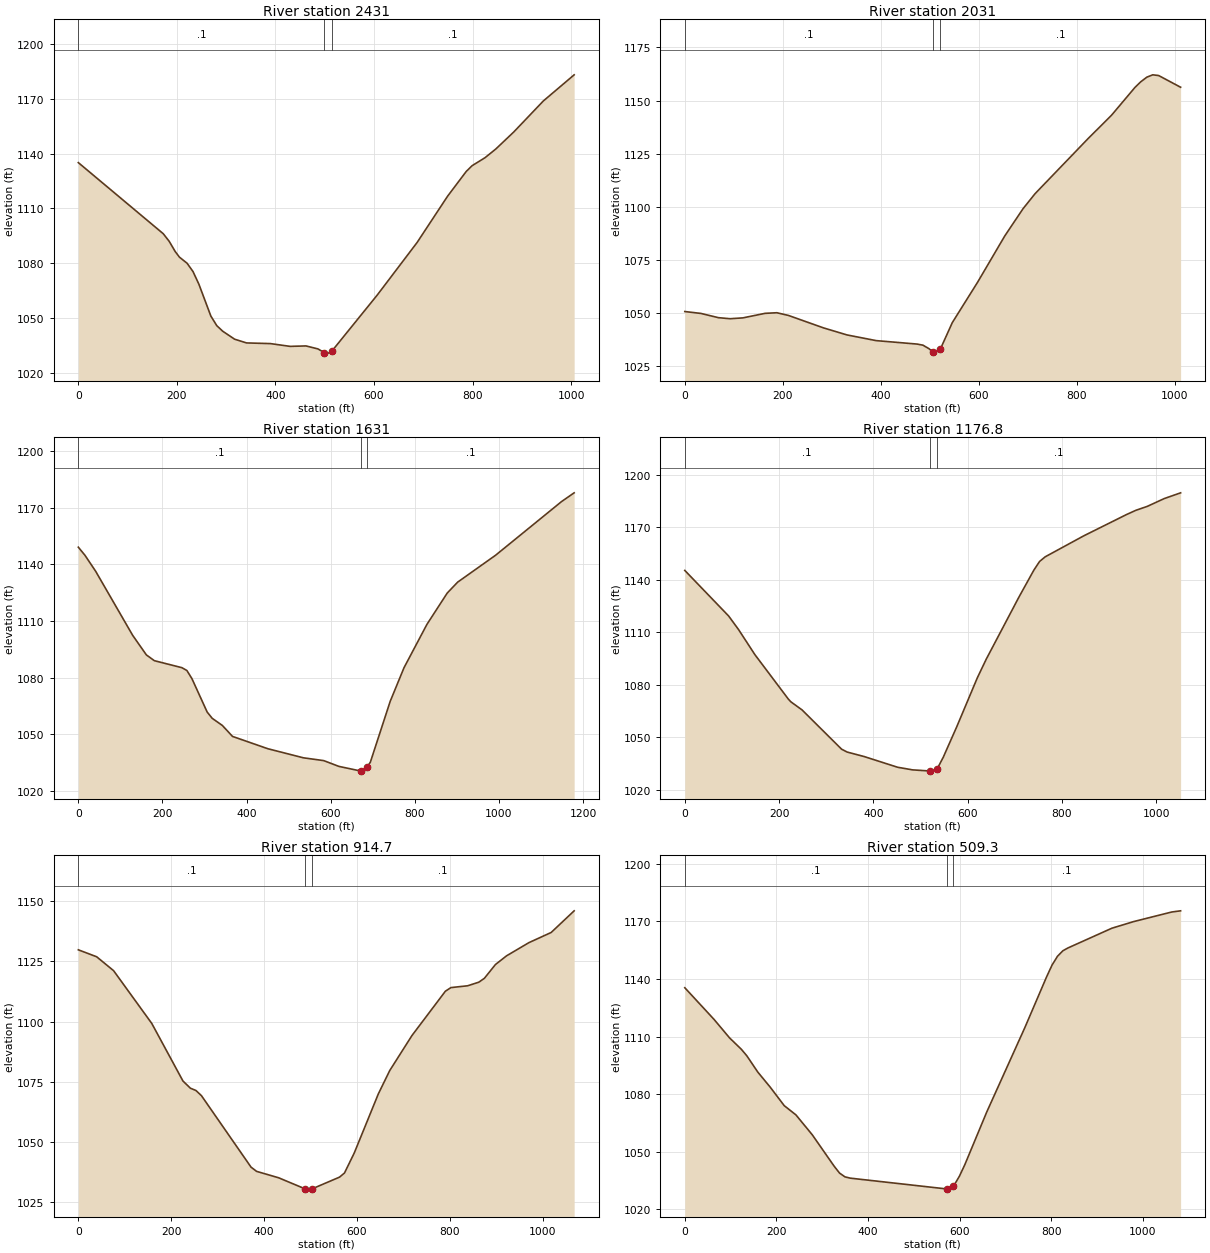
Type RM Length L Ch R = 1 ,2431    ,401.834,400,400.1
XS GIS Cut Line= 3
     1686306.902       268673.33     1686397.885      268174.947
     1686478.634      267682.098
#Sta/Elev= 30
       0 1135.05   172.3 1096.21   184.4 1092.05   196.5  1086.5   205.2  1083.4
   220.6  1080.1   232.7 1075.54   244.7 1068.58   268.9 1051.24   280.9    1046
     293 1042.95   317.1  1038.6   341.3 1036.56   389.6  1036.2   429.7 1034.68
     462 1034.92   486.1  1033.3   499.1 1031.27   510.2 1030.99   514.1 1031.98
   606.5 1062.72   687.2 1091.37   749.2  1116.7     787 1130.21     799 1133.38
   825.1 1137.72   847.1  1142.5   883.2 1151.71   943.4  1168.7    1006    1183
#Mann= 3 , 0 , 0
       0      .1       0   499.1    .045       0   514.1      .1       0
Bank Sta=499.1,514.1
XS Rating Curve= 0 ,0
Exp/Cntr=0.3,0.1

Type RM Length L Ch R = 1 ,2031    ,398.428,400,402.553
XS GIS Cut Line= 3
     1686730.346      268750.229     1686781.368      268238.349
      1686864.15      267747.233
#Sta/Elev= 30
       0 1050.81    32.9 1049.92    68.7 1047.92    92.5 1047.43   118.5 1047.82
   164.1 1049.96     188 1050.24   211.8 1048.96   283.4 1043.11   331.2 1039.81
   390.8 1037.13   474.3 1035.51   486.3 1034.99   498.2  1033.4   506.9  1031.8
   510.1 1031.25   521.9 1033.16   546.2 1045.57     598 1064.62   653.6 1086.43
   690.7 1099.16   715.4 1106.26   823.1 1132.03   871.3 1143.09   919.5 1156.26
   931.1 1158.84   943.5 1161.02   955.6 1162.12   967.6 1161.79  1012.5 1156.28
#Mann= 3 , 0 , 0
       0      .1       0   506.9    .045       0   521.9      .1       0
Bank Sta=506.9,521.9
XS Rating Curve= 0 ,0
Exp/Cntr=0.3,0.1

Type RM Length L Ch R = 1 ,1631    ,462.155,454.217,443.365
XS GIS Cut Line= 3
     1687039.492      269043.192      1687153.36      268374.103
     1687290.052      267893.197
#Sta/Elev= 30
       0 1149.03      16 1144.66    41.3 1136.24   129.2 1102.36   161.8 1091.99
   180.7 1088.94   246.1 1085.24   258.1 1083.73   270.1 1079.41   306.3 1061.73
   318.3 1058.41   342.4 1054.64   366.5 1048.84   450.8  1042.3   535.1 1037.51
   583.3 1036.03   619.4 1032.97   671.2 1030.52   674.7 1030.46   678.7 1030.61
   686.2 1032.57   694.2 1035.19   741.4 1067.41   774.2  1085.2   828.7 1108.16
   877.1 1124.78   901.8 1130.53   992.1 1144.79  1148.7 1173.17  1178.7 1177.81
#Mann= 3 , 0 , 0
       0      .1       0   671.2    .045       0   686.2      .1       0
Bank Sta=671.2,686.2
XS Rating Curve= 0 ,0
Exp/Cntr=0.3,0.1

Type RM Length L Ch R = 1 ,1176.8  ,260.804,262.098,262.334
XS GIS Cut Line= 3
     1687575.828      268904.701     1687504.097       268377.85
     1687422.128       267863.91
#Sta/Elev= 30
       0 1145.35      93 1119.32     114 1111.59   148.7 1097.25   219.5 1071.91
   224.9 1070.31   248.8 1065.65   332.7 1043.21   344.7 1041.55   380.6    1039
   451.5 1032.89   483.2 1031.39   519.6 1030.75   524.4 1030.67   534.6 1032.11
   536.4  1032.4   548.4 1038.58   577.3 1056.16   620.6  1083.9   639.5 1094.56
   708.9 1130.06   740.8 1145.57   752.8 1150.46   764.8 1153.14   846.9 1165.16
   937.7 1177.33   957.2 1179.71   981.3 1181.94  1017.3  1186.4  1052.1 1189.69
#Mann= 3 , 0 , 0
       0      .1       0   519.6    .045       0   534.6      .1       0
Bank Sta=519.6,534.6
XS Rating Curve= 0 ,0
Exp/Cntr=0.3,0.1

Type RM Length L Ch R = 1 ,914.7   ,401.752,405.35,409.864
XS GIS Cut Line= 3
     1687780.503      268863.831     1687764.168      268377.601
     1687681.584      267801.814
#Sta/Elev= 30
       0 1129.78    39.5 1126.89      76 1121.12   158.3 1099.22   225.4 1075.36
   241.4 1072.38   253.3 1071.43   265.2 1069.29   372.1 1039.63     384 1037.88
   431.5 1035.22   488.3 1030.64   490.9 1030.51   503.3  1030.6   562.7 1035.48
   573.4  1037.2   594.4 1045.48   646.3    1070   670.9  1079.7   718.8 1094.23
   790.8 1112.61   802.8 1114.11   838.8 1114.86   862.8 1116.35   874.8 1117.96
   898.6 1123.67   922.7  1127.3   970.7 1132.75  1018.7 1136.97  1068.2 1145.95
#Mann= 3 , 0 , 0
       0      .1       0   488.3    .045       0   503.3      .1       0
Bank Sta=488.3,503.3
XS Rating Curve= 0 ,0
Exp/Cntr=0.3,0.1

Type RM Length L Ch R = 1 ,509.3   ,315.64,314.25,313.428
XS GIS Cut Line= 3
     1687974.063      268757.569     1688014.319      268178.446
     1688035.935      267677.217
#Sta/Elev= 30
       0 1135.46      64 1118.91    97.7 1109.33   123.5 1103.37   135.4 1099.99
   159.2 1091.55   186.8 1083.54     217 1074.02   242.5 1069.21   278.2 1058.84
   325.8 1042.53   337.7 1038.89   349.6  1036.9   361.5 1036.22   571.4 1030.61
   575.7 1030.51   586.4 1031.96   599.5  1037.3   611.4 1043.36   658.9 1070.62
   742.1 1114.63   789.6 1141.09   801.5 1147.23   813.4 1151.85   825.3 1154.74
   836.1 1156.17   932.2 1166.48   979.8 1169.94  1062.9 1174.93  1082.2 1175.54
#Mann= 3 , 0 , 0
       0      .1       0   571.4    .045       0   586.4      .1       0
Bank Sta=571.4,586.4
XS Rating Curve= 0 ,0
Exp/Cntr=0.3,0.1

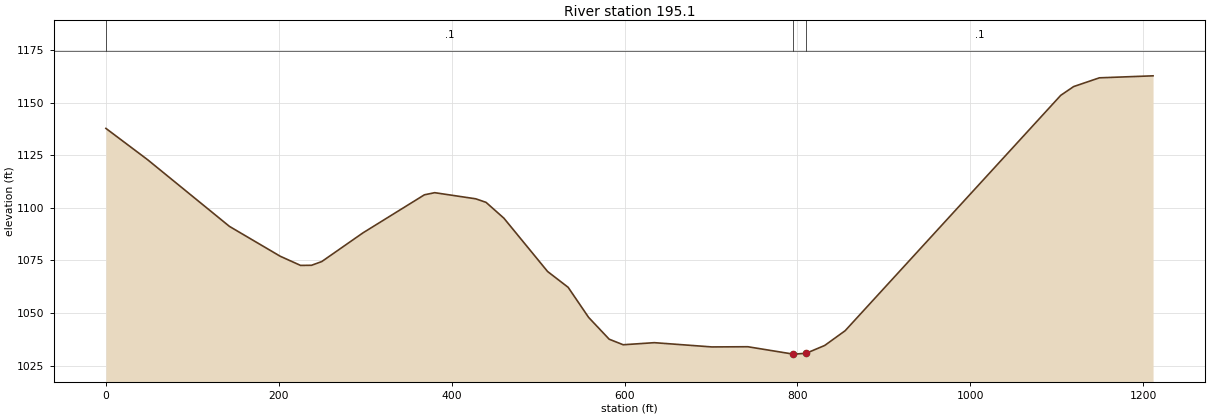
Type RM Length L Ch R = 1 ,195.1   ,175.841,195.057,214.256
XS GIS Cut Line= 3
       1688324.5      268967.315     1688316.844      268154.946
      1688313.64      267755.307
#Sta/Elev= 30
       0 1137.76      48 1122.96     143 1091.18   201.7 1077.01   225.2 1072.66
   237.9 1072.72   249.8  1074.5   297.3 1088.09   368.5  1106.2   380.4 1107.21
   427.9  1104.3   439.8 1102.62   460.5 1095.08     511 1069.77   534.8 1062.25
   558.5 1047.95   582.3 1037.59   598.5 1034.96   634.5 1035.95     701 1033.93
   742.7 1034.02   795.1 1030.52     796 1030.51   810.1 1030.91   831.6 1034.62
   855.3 1041.64  1104.7 1153.46  1119.6 1157.62  1149.4 1161.78  1211.5 1162.73
#Mann= 3 , 0 , 0
       0      .1       0   795.1    .045       0   810.1      .1       0
Bank Sta=795.1,810.1
XS Rating Curve= 0 ,0
Exp/Cntr=0.3,0.1

Chan Stop Cuts=-1
Use User Specified Reach Order=0